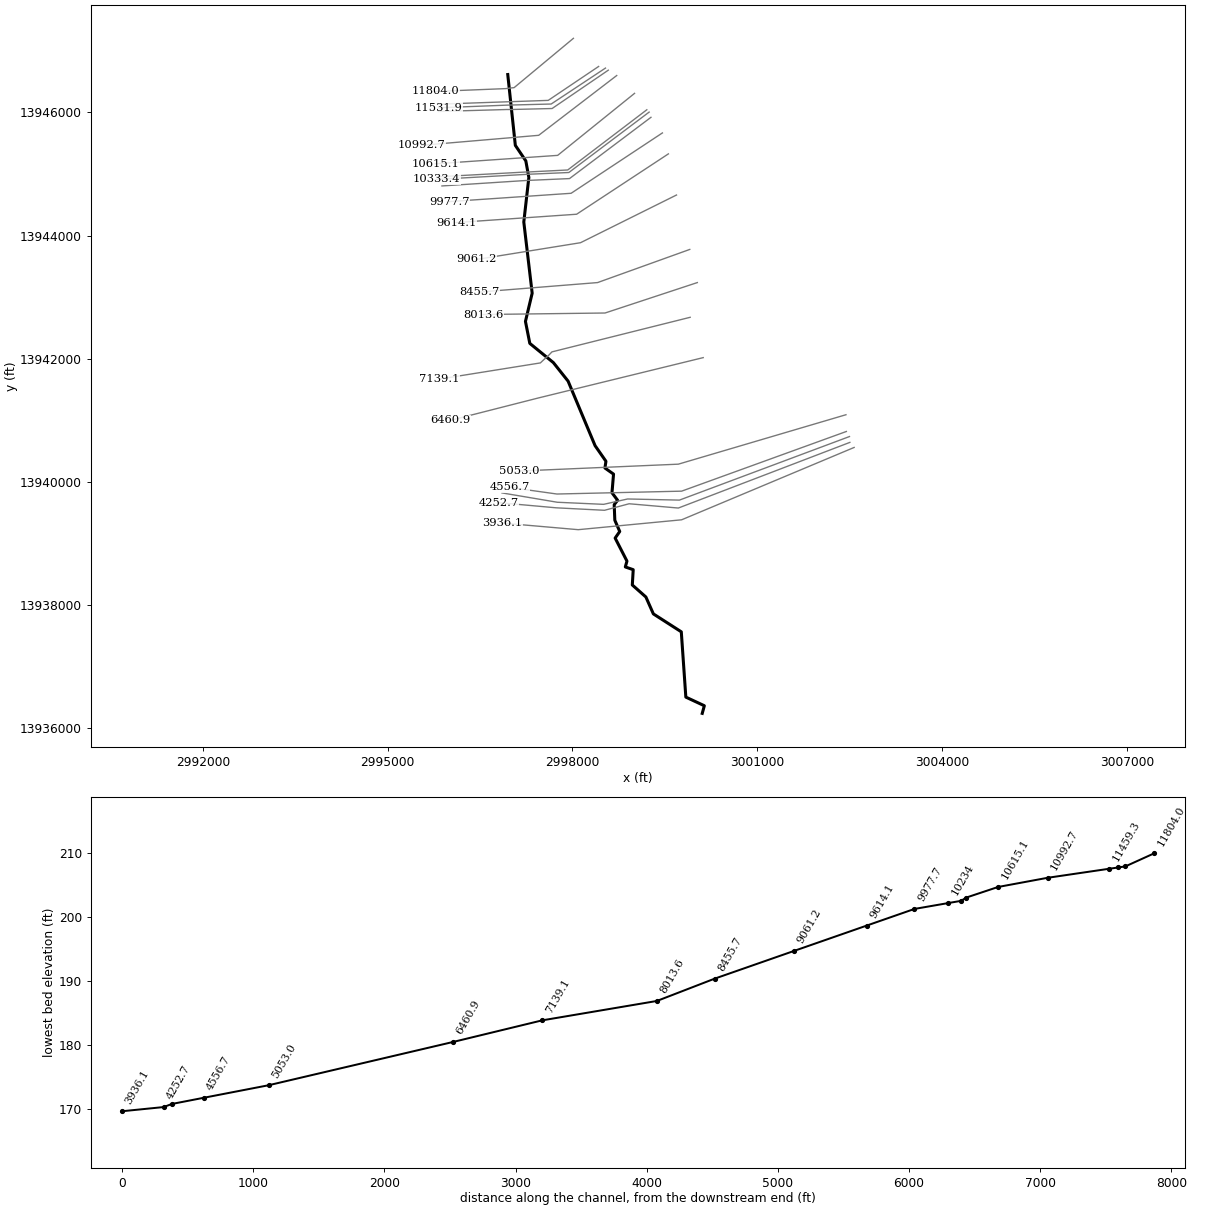
--- L112-00-00.PRJ (project) ---

Proj Title=L112-00-00
Current Plan=p03
Default Exp/Contr=.3,.1
English Units
Geom File=g01
Flow File=f02
Flow File=f03
Plan File=p02
Plan File=p03
Y Axis Title=Elevation
X Axis Title(PF)=Main Channel Distance
X Axis Title(XS)=Station
BEGIN DESCRIPTION:
Little Cypress Creek
Tributary 10.99 to Little Cypress
HCFCD Unit L112-00-00
Flood Hazard Model
10, 2, 1, 0.50-% Event
Filename L114-01-00.prj
Prepared by: Halff Associates, Inc. Date: 03/24/2004
Reviewed by: ______________    Date: __________
STATUS Final RAS
END DESCRIPTION:
DSS File=dss
DSS Export Rating Curves= 0
DSS Export Rating Curve Sorted= 0
DSS Export Volume Flow Curves= 0
DXF OffsetX= 0
DXF OffsetY= 0
DXF ScaleX= 1
DXF ScaleY= 10

--- L112-00-00.p03 (plan) ---

Plan Title=Floodway
Version=Version 3.0.1  Mar 2001
Short Identifier=Floodway0607
Geom File=g01
Flow File=f03
Subcritical Flow
K Sum by GR= 0
Std Step Tol= 0.01
Critical Tol= 0.01
Num of Std Step Trials= 20
Max Error Tol= 0.3
Flow Tol Ratio= 0.001
Split Flow NTrial= 30
Split Flow Tol= 0.02
Split Flow Ratio= 0.02
Log Output Level= 0
Friction Slope Method= 1
Unsteady Friction Slope Method= 2
Parabolic Critical Depth
Global Vel Dist= 0 , 0 , 0
Global Log Level= 0
CheckData=True
Encroach Param=-1 ,0,0, 2
Encroach River=L112-00-00
Encroach Reach=Reach - 1
Encroach Node=11804.0
       1    4790    5090
Encroach Node=11586.2
       1    4795    5085
Encroach Node=11555
       1    4795    5085
Encroach Node=11531.9
       1    4795    5085
Encroach Node=11459.3
       1    4795    5095
Encroach Node=10992.7
       1    4820    5225
Encroach Node=10615.1
       1    4862    5250
Encroach Node=10371.2
       1    4875    5100
Encroach Node=10350
       1    4875    5100
Encroach Node=10333.4
       1    4875    5100
Encroach Node=10234
       1    4870    5105
Encroach Node=9977.7
       1 4886.12    5135
Encroach Node=9614.1
       1    4830  5153.3
Encroach Node=9061.2
       1    4800 5106.25
Encroach Node=8455.7
       1    4900    5050
Encroach Node=8013.6
       1    4717    5115
Encroach Node=7139.1
       1  4974.1    5500
Encroach Node=6460.9
       1 4758.61    5300
Encroach Node=5053.0
       1    4560    5170
Encroach Node=4556.7
       1    4500    5185
Encroach Node=4314.7
       1    4500    5300
Encroach Node=4283.7
       1    4500    5300
Encroach Node=4252.7
       1    4500    5300
Encroach Node=3936.1
       1    4500    5350
Encroach Node=3704.0
       1    4500    5270
Encroach Node=3553.6
       1    4630 5178.35
Encroach Node=3521.6
       1    4630 5178.35
Encroach Node=3489.6
       1    4630 5178.35
Encroach Node=3231.5
       1    4695  5306.5
Encroach Node=2149.6
       1    4720    5140
Encroach Node=1379.8
       1    4720  5592.6
Encroach Reach=L112-00-00_0014
Encroach Node=11804.0
       1    4790    5090
Encroach Node=11586.2
       1    4795    5085
Encroach Node=11555
       1    4795    5085
Encroach Node=11531.9
       1    4795    5085
Encroach Node=11459.3
       1    4795    5095
Encroach Node=10992.7
       1    4820    5225
Encroach Node=10615.1
       1    4862    5250
Encroach Node=10371.2
       1    4875    5100
Encroach Node=10350
       1    4875    5100
Encroach Node=10333.4
       1    4875    5100
Encroach Node=10234
       1    4870    5105
Encroach Node=9977.7
       1 4886.12    5135
Encroach Node=9614.1
       1    4830  5153.3
Encroach Node=9061.2
       1    4800 5106.25
Encroach Node=8455.7
       1    4900    5050
Encroach Node=8013.6
       1    4717    5115
Encroach Node=7139.1
       1  4974.1    5500
Encroach Node=6460.9
       1 4758.61    5300
Encroach Node=5053.0
       1    4560    5170
Encroach Node=4556.7
       1    4500    5185
Encroach Node=4314.7
       1    4500    5300
Encroach Node=4283.7
       1    4500    5300
Encroach Node=4252.7
       1    4500    5300
Encroach Node=3936.1
       1    4500    5350
Encroach Node=3704.0
       1    4500    5270
Encroach Node=3553.6
       1    4630 5178.35
Encroach Node=3521.6
       1    4630 5178.35
Encroach Node=3489.6
       1    4630 5178.35
Encroach Node=3231.5
       1    4695  5306.5
Encroach Node=2149.6
       1    4720    5140
Encroach Node=1379.8
       1    4720  5592.6
Computation Interval=1HOUR
Output Interval=1HOUR
Run HTab= 0
Run UNet= 0
Run PostProcess= 0
UNET Theta= 1
UNET ZTol= 0.02
UNET ZSATol= 0.1
UNET MxIter= 20
UNET MaxInSteps= 20
UNET DtIC= 0
UNET DtMin= 0
UNET MaxCRTS= 20
UNET WFStab= 2
UNET SFStab= 1
UNET WFX= 1
UNET SFX= 1
UNET Convert EG Bridges=-1
UNET Use Existing IB Tables=-1
Instantaneous Interval=1HOUR
DSS File=dss
Write IC File= 0
Write Velocity= 0
Write Detailed= 0

--- L112-00-00.p02 (plan) ---

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Plan Title=FEMA Effective June 2007
Short Identifier=FEMAeff0607
Geom File=g01
Flow File=f02
Encroach Param=-1 ,0,0, 0

--- L112-00-00.f03 (steady flow) ---

Flow Title=Floodway
Version=Version 3.0.1  Mar 2001
Number of Profiles= 2
Profile Names=1PCT_100yr,1PCTFloodway_100yrFW
River Rch & RM=L112-00-00,L112-00-00_0014 ,11804.0
     860     860
River Rch & RM=L112-00-00,L112-00-00_0014 ,10992.7
     900     900
River Rch & RM=L112-00-00,L112-00-00_0014 ,10333.4
     930     930
River Rch & RM=L112-00-00,L112-00-00_0014 ,9977.7
     960     960
River Rch & RM=L112-00-00,L112-00-00_0014 ,9614.1
    1000    1000
River Rch & RM=L112-00-00,L112-00-00_0014 ,9061.2
    1060    1060
River Rch & RM=L112-00-00,L112-00-00_0014 ,8455.7
    1110    1110
River Rch & RM=L112-00-00,L112-00-00_0014 ,8013.6
    1190    1190
River Rch & RM=L112-00-00,L112-00-00_0014 ,6460.9
    1250    1250
River Rch & RM=L112-00-00,L112-00-00_0014 ,5053.0
    3370    3370
River Rch & RM=L112-00-00,L112-00-00_0014 ,3553.6
    3520    3520
River Rch & RM=L112-00-00,L112-00-00_0014 ,2149.6
    3614    3614
Boundary for River Rch & Prof#=L112-00-00,L112-00-00_0014 , 1
Up Type= 0
Dn Type= 3
Dn Slope=.0021
Boundary for River Rch & Prof#=L112-00-00,L112-00-00_0014 , 2
Up Type= 0
Dn Type= 1
Dn Known WS=175.65
DSS Import GetInterval= 0
DSS Import GetPeak= 0
DSS Import FillOption= 0

--- L112-00-00.f02 (steady flow) ---

Flow Title=FEMA Effective June 2007
Version=Version 3.0.1  Mar 2001
Number of Profiles= 4
Profile Names=10PCT_10yr,2PCT_50yr,1PCT_100yr,0.2PCT_500yr
River Rch & RM=L112-00-00,L112-00-00_0014 ,11804.0
     460     710     860    1400
River Rch & RM=L112-00-00,L112-00-00_0014 ,10992.7
     480     750     900    1480
River Rch & RM=L112-00-00,L112-00-00_0014 ,10333.4
     500     780     930    1520
River Rch & RM=L112-00-00,L112-00-00_0014 ,9977.7
     520     810     960    1580
River Rch & RM=L112-00-00,L112-00-00_0014 ,9614.1
     550     850    1000    1650
River Rch & RM=L112-00-00,L112-00-00_0014 ,9061.2
     570     890    1060    1690
River Rch & RM=L112-00-00,L112-00-00_0014 ,8455.7
     590     920    1110    1720
River Rch & RM=L112-00-00,L112-00-00_0014 ,8013.6
     630     960    1190    1770
River Rch & RM=L112-00-00,L112-00-00_0014 ,6460.9
     650    1000    1250    1800
River Rch & RM=L112-00-00,L112-00-00_0014 ,5053.0
    1790    2890    3370    5180
River Rch & RM=L112-00-00,L112-00-00_0014 ,3553.6
    1820    2960    3520    5340
River Rch & RM=L112-00-00,L112-00-00_0014 ,2149.6
    1834    3005    3614    5431
Boundary for River Rch & Prof#=L112-00-00,L112-00-00_0014 , 1
Up Type= 0
Dn Type= 3
Dn Slope=.0021
Boundary for River Rch & Prof#=L112-00-00,L112-00-00_0014 , 2
Up Type= 0
Dn Type= 3
Dn Slope=.0021
Boundary for River Rch & Prof#=L112-00-00,L112-00-00_0014 , 3
Up Type= 0
Dn Type= 3
Dn Slope=.0021
Boundary for River Rch & Prof#=L112-00-00,L112-00-00_0014 , 4
Up Type= 0
Dn Type= 3
Dn Slope=.0021
DSS Import GetInterval= 0
DSS Import GetPeak= 0
DSS Import FillOption= 0

--- L112-00-00.g01 (geometry) ---

Geom Title=L112-00-00 June 2007
Version=Version 3.0.1  Mar 2001

River Reach=L112-00-00      ,L112-00-00_0014
Reach XY= 30
      2996950.42   13946613.8701    2997073.4034   13945464.1684
    2997243.5605   13945212.0835     2997292.736   13944943.0399
    2997210.7624   13944219.9311    2997346.6906   13943064.7156
    2997237.5217   13942606.7487    2997308.3781   13942249.9409
     2997690.329   13941938.3701    2997929.7615   13941637.1066
    2998367.8821   13940589.5524    2998544.1305   13940336.3516
    2998527.6375   13940226.9766    2998667.3944   13940128.0183
    2998642.2208   13939825.0669    2998733.3667   13939703.5391
    2998678.1345   13939632.1423    2998688.2278   13939379.7544
    2998768.0889   13939196.5946    2998693.4361   13939089.8238
    2998885.2764   13938715.6919    2998858.3667   13938621.0738
    2998986.8389    13938576.803    2998972.0819   13938328.5391
     2999192.568   13938133.2266    2999314.0958    13937858.921
    2999767.2208   13937568.1224    2999841.0055   13936508.2266
    3000141.3528   13936368.4696    3000107.1218   13936244.3835

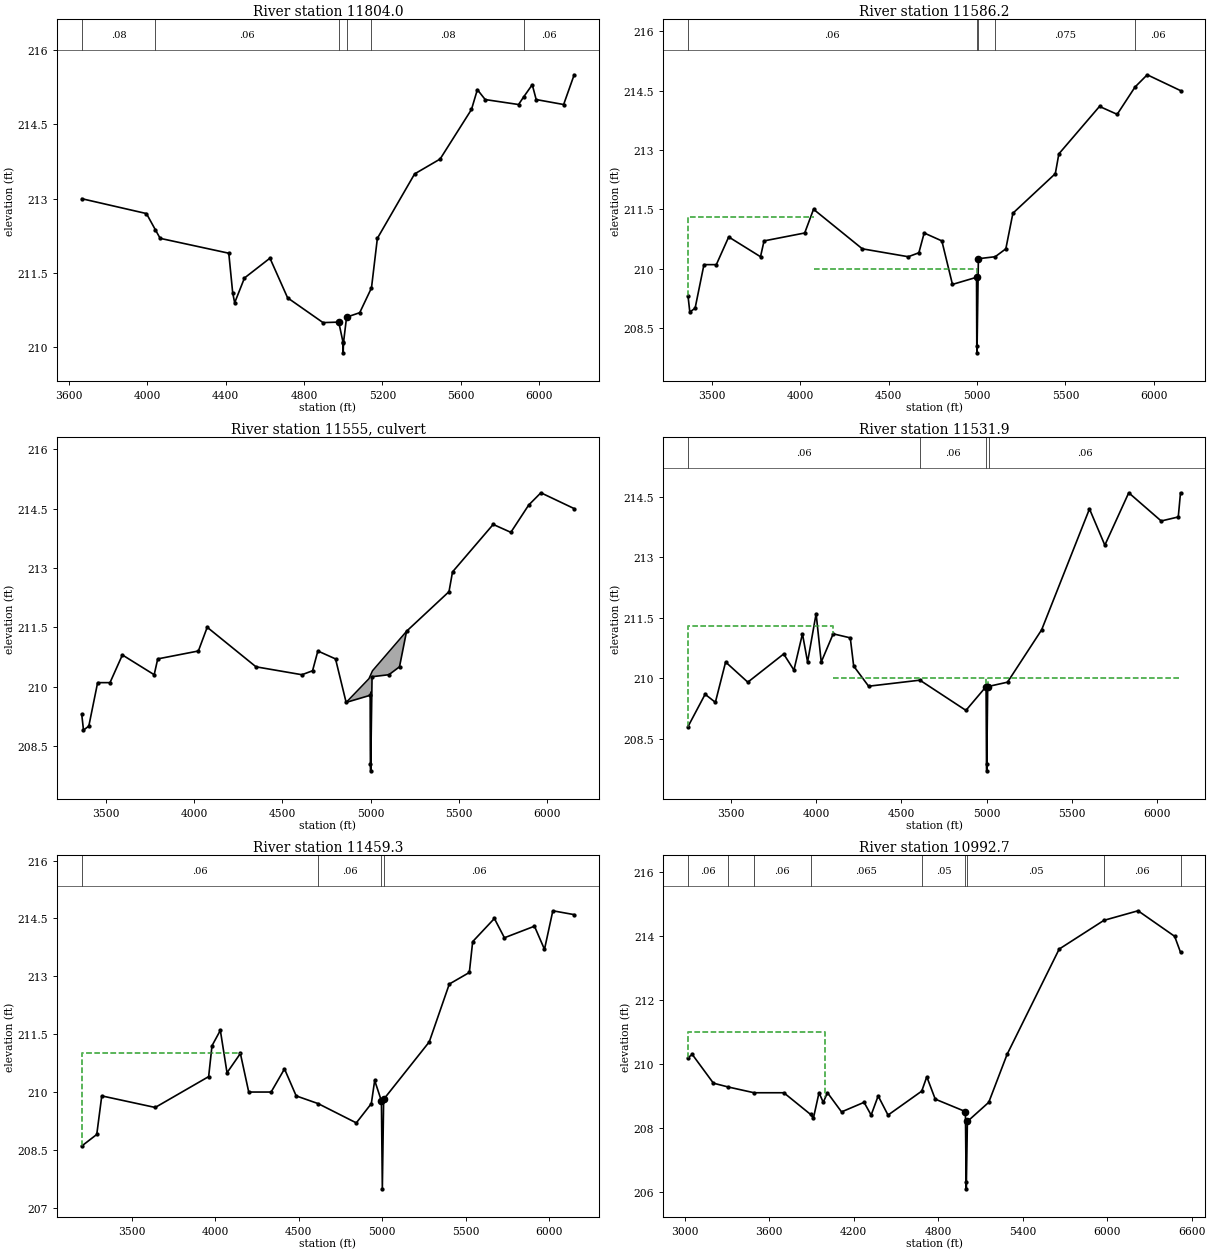
Type RM Length L Ch R = 1 ,11804.0 ,286.7,217.8,215.1
BEGIN DESCRIPTION:
Cross Section XS15
END DESCRIPTION:
XS GIS Cut Line= 4
      2998015.92     13947201.47      2997054.23     13946401.77
      2996918.18     13946385.41      2995775.31      13946339.6
#Sta/Elev= 30
  3666.4     213  3996.4   212.7  4042.4  212.37  4066.4   212.2  4416.4   211.9
  4436.4   211.1  4446.4   210.9  4496.4   211.4  4626.4   211.8  4716.4     211
  4897.1   210.5  4977.2  210.51  4998.7  210.11  4999.9  209.89  5001.3  210.09
  5017.2  210.61  5084.2   210.7  5144.2   211.2  5174.2   212.2  5364.2   213.5
  5494.2   213.8  5654.2   214.8  5684.2   215.2  5724.2     215  5894.2   214.9
  5919.8  215.05  5964.2   215.3  5984.2     215  6124.2   214.9    6178   215.5
#Mann= 6 ,-1 , 0
  3666.4     .08       0  4042.4     .06       0  4977.2    .045       0
  5017.2     .06       0  5144.2     .08       0  5919.8     .06       0
Bank Sta=4977.2,5017.2
XS Rating Curve= 0
Exp/Cntr=.5,.3

Type RM Length L Ch R = 1 ,11586.2 ,56.5,54.3,54.1
BEGIN DESCRIPTION:
Upstream Section of Bridge/Culvert/Weir
Cross Section XS14.7
END DESCRIPTION:
XS GIS Cut Line= 5
      2998425.29     13946744.87      2997607.24     13946194.35
       2996966.9      13946172.1      2996915.72     13946170.59
       2995808.1     13946132.22
#Sta/Elev= 30
    3365   209.3    3375   208.9    3405     209    3455   210.1    3525   210.1
    3595   210.8    3775   210.3    3795   210.7    4025   210.9    4075   211.5
    4351   210.5    4611   210.3    4671   210.4    4701   210.9    4801   210.7
    4861   209.6 4997.23  209.78  4998.7  208.04  4999.9  207.87  5007.7  210.25
    5103   210.3    5163   210.5    5203   211.4    5443   212.4    5463   212.9
    5693   214.1    5793   213.9  5893.9  214.59    5963   214.9  6151.3   214.5
#Mann= 5 ,-1 , 0
    3365     .06       0 4997.23    .045       0  5007.7     .06       0
    5103    .075       0  5893.9     .06       0
#XS Ineff= 3 ,-1
    3365    4080   211.3    4080 4997.23     210  5007.7  6151.3     210
Permanent Ineff=
       F       F       F
Bank Sta=4997.23,5007.7
XS Rating Curve= 0
Exp/Cntr=.5,.3

Type RM Length L Ch R = 2 ,11555   ,,,
BEGIN DESCRIPTION:
Plaza 290
END DESCRIPTION:
Bridge Culvert--1,0,-1,-1, 0
Deck Dist Width WeirC Skew NumUp NumDn MinLoCord MaxHiCord MaxSubmerge Is_Ogee
10,30,2.6,0, 4, 6, , , .95, 0, 0,0,,
    4861    4990    5010    5203
   209.6   210.2   210.4   211.4
                                
  4838.3    4861    4990    5010    5203  5361.7
   209.5   209.6   210.2   210.4   211.4   211.7
                                                
Culvert=1,2,,30,.015,.5,1,1,1,207.87,5000,207.71,5000,Culvert #1  , 0 ,15
Culvert Bottom n=.015
BC Design=,, 0 ,, 0 ,,,,,,

Type RM Length L Ch R = 1 ,11531.9 ,73.5,72.6,70.9
BEGIN DESCRIPTION:
Downstream Section of Bridge/Culvert/Weir
Cross Section XS14.5
END DESCRIPTION:
XS GIS Cut Line= 5
      2998536.74     13946718.88      2997655.01     13946135.19
      2996977.73     13946118.23      2996941.84     13946117.26
      2995829.62     13946074.08
#Sta/Elev= 30
  3250.9   208.8  3350.9   209.6  3410.9   209.4  3470.9   210.4  3600.9   209.9
  3810.9   210.6  3870.9   210.2  3920.9   211.1  3950.9   210.4  4000.9   211.6
  4030.9   210.4  4100.9   211.1  4200.9     211  4220.9   210.3  4308.3   209.8
  4608.6  209.95  4878.3   209.2 4996.11  209.79  4998.7  207.87  4999.9   207.7
 5005.77  209.79  5015.8   209.8  5121.7   209.9  5321.7   211.2  5601.7   214.2
  5691.7   213.3  5831.7   214.6  6021.7   213.9  6121.7     214  6134.8   214.6
#Mann= 4 ,-1 , 0
  3250.9     .06       0  4608.6     .06       0 4996.11    .045       0
  5015.8     .06       0
#XS Ineff= 3 ,-1
  3250.9    4100   211.3    4100 4996.11     210 5005.77  6134.8     210
Permanent Ineff=
       F       F       F
Bank Sta=4996.11,5005.77
XS Rating Curve= 0
Exp/Cntr=.5,.3

Type RM Length L Ch R = 1 ,11459.3 ,445,466.6,466.7
BEGIN DESCRIPTION:
Cross Section XS14.3
END DESCRIPTION:
XS GIS Cut Line= 5
      2998582.27     13946684.64      2997670.29     13946062.31
      2997004.45     13946046.08      2996933.68     13946046.08
      2995826.29     13946014.38
#Sta/Elev= 30
  3199.9   208.6  3289.9   208.9  3319.9   209.9  3639.9   209.6  3959.9   210.4
  3979.9   211.2  4029.9   211.6  4069.9   210.5  4149.9     211  4199.9     210
    4334     210    4414   210.6    4484   209.9  4615.5   209.7    4844   209.2
    4934   209.7    4954   210.3 4994.36  209.77  4999.9  207.49  5007.7  209.81
  5280.8   211.3  5400.8   212.8  5520.8   213.1  5540.8   213.9  5670.8   214.5
  5730.8     214  5910.8   214.3  5970.8   213.7  6020.8   214.7  6148.6   214.6
#Mann= 4 ,-1 , 0
  3199.9     .06       0  4615.5     .06       0 4994.36    .045       0
  5007.7     .06       0
#XS Ineff= 2 , 0
       0    4150     211               0
Permanent Ineff=
       F       F
Bank Sta=4994.36,5007.7
XS Rating Curve= 0
Exp/Cntr=.3,.1

Type RM Length L Ch R = 1 ,10992.7 ,347.53,377.6,352.59
BEGIN DESCRIPTION:
Left Ineffective used to transition with upstream and downstream cross sections
Cross Section XS14
END DESCRIPTION:
XS GIS Cut Line= 3
    2998718.9001   13946597.7365    2997452.5985   13945627.3931
     2995557.989   13945465.4606
#Sta/Elev= 30
  3024.1   210.2  3054.1   210.3  3204.1   209.4  3309.4  209.28  3492.9   209.1
  3704.1   209.1  3894.4  208.42  3914.1   208.3  3954.1   209.1  3984.1   208.8
  4014.1   209.1  4114.1   208.5  4274.1   208.8  4324.1   208.4  4374.1     209
  4444.1   208.4  4683.3  209.15  4719.4   209.6  4779.4   208.9  4993.7  208.51
  4998.7  206.31  4999.9  206.09  5007.7   208.2  5159.4   208.8  5289.4   210.3
  5659.4   213.6  5977.1   214.5  6219.4   214.8  6479.4     214    6521   213.5
#Mann= 9 ,-1 , 0
  3024.1     .06       0  3309.4    .075       0  3492.9     .06       0
  3894.4    .065       0  4683.3     .05       0  4993.7    .045       0
  5007.7     .05       0  5977.1     .06       0    6521      .2       0
#XS Ineff= 2 , 0
       0    4000     211               0
Permanent Ineff=
       F       F
Bank Sta=4993.7,5007.7
XS Rating Curve= 0
Exp/Cntr=.3,.1

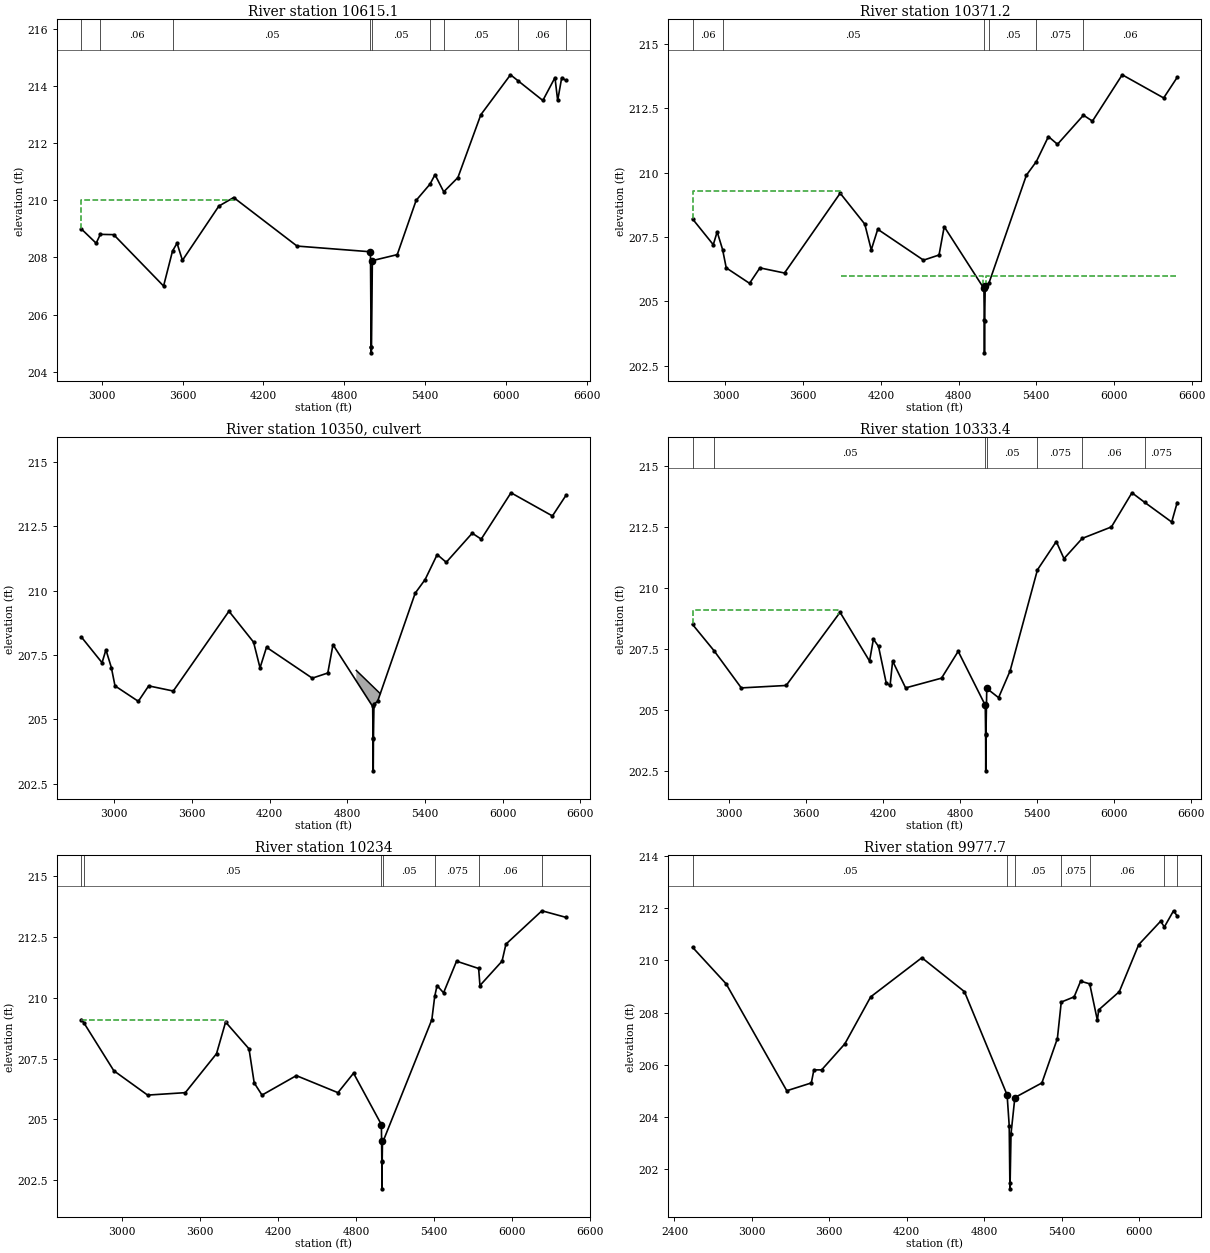
Type RM Length L Ch R = 1 ,10615.1 ,245.3,243.9,238.5
BEGIN DESCRIPTION:
Cross Section XS13.5
END DESCRIPTION:
XS GIS Cut Line= 3
    2999008.3625   13946308.2741    2997760.2863   13945301.7328
    2995773.4722   13945164.7321
#Sta/Elev= 30
    2849     209    2959   208.5  2989.8  208.81    3089   208.8    3459     207
  3525.6  208.23    3559   208.5    3599   207.9    3869   209.8    3979   210.1
    4449   208.4  4993.7   208.2  4998.7  204.88  4999.9  204.66  5001.3  204.88
  5007.7  207.89  5192.4   208.1  5332.4     210  5435.5  210.57  5472.4   210.9
  5537.3   210.3  5642.4   210.8  5812.4     213  6032.4   214.4  6088.5  214.19
  6272.4   213.5  6362.4   214.3  6382.4   213.5  6412.4   214.3  6443.9   214.2
#Mann= 9 ,-1 , 0
    2849    .075       0  2989.8     .06       0  3525.6     .05       0
  4993.7    .045       0  5007.7     .05       0  5435.5    .075       0
  5537.3     .05       0  6088.5     .06       0  6443.9      .2       0
#XS Ineff= 2 , 0
       0    3980     210               0
Permanent Ineff=
       F       F
Bank Sta=4993.7,5007.7
XS Rating Curve= 0
Exp/Cntr=.5,.3

Type RM Length L Ch R = 1 ,10371.2 ,38.5,37.8,37.7
BEGIN DESCRIPTION:
Upstream Section of Bridge/Culvert/Weir
Cross Section XS13.1
END DESCRIPTION:
XS GIS Cut Line= 5
      2999207.59     13946041.99      2997923.88     13945064.75
       2997300.5      13945033.2      2997249.89     13945032.05
      2995797.54     13944952.72
#Sta/Elev= 30
  2745.7   208.2  2905.7   207.2  2935.7   207.7  2977.6  207.01  3005.7   206.3
  3185.7   205.7  3265.7   206.3  3455.7   206.1  3885.7   209.2  4075.7     208
  4125.7     207  4175.7   207.8  4529.1   206.6  4649.1   206.8  4689.1   207.9
 4995.71   205.5  4998.7  204.26  4999.9     203  5001.3  204.24 5005.73  205.59
  5033.9   205.7  5323.9   209.9  5400.7  210.43  5493.9   211.4  5563.9   211.1
  5764.4  212.23  5833.9     212  6063.9   213.8  6383.9   212.9  6488.4   213.7
#Mann= 6 ,-1 , 0
  2745.7     .06       0  2977.6     .05       0 4995.71    .045       0
  5033.9     .05       0  5400.7    .075       0  5764.4     .06       0
#XS Ineff= 3 ,-1
  2745.7    3890   209.3    3890    4989     206    5011  6488.4     206
Permanent Ineff=
       F       F       F
Bank Sta=4995.71,5005.73
XS Rating Curve= 0
Exp/Cntr=.5,.3

Type RM Length L Ch R = 2 ,10350   ,,,
BEGIN DESCRIPTION:
Private Road DS of Plaza 290
END DESCRIPTION:
Bridge Culvert--1,0,-1,-1, 0
Deck Dist Width WeirC Skew NumUp NumDn MinLoCord MaxHiCord MaxSubmerge Is_Ogee
10,20,2.6,0, 2, 2, , , .95, 0, 0,0,,
  4869.1  5053.9
   206.9     206
                
  4874.9  5029.8
   206.6   205.9
                
Culvert=1,2,,20,.015,.5,1,1,1,203,5000,202.5,5000,Culvert #1  , 0 ,10
Culvert Bottom n=.015
BC Design=,, 0 ,, 0 ,,,,,,

Type RM Length L Ch R = 1 ,10333.4 ,100,99.4,99.4
BEGIN DESCRIPTION:
Downstream Section of Bridge/Culvert/Weir
Cross Section XS13
END DESCRIPTION:
XS GIS Cut Line= 5
      2999245.39     13946004.34      2997941.95     13945023.58
      2997305.89      13944996.1       2997267.7     13944994.19
      2995797.24     13944911.58
#Sta/Elev= 30
  2713.7   208.5  2880.3  207.43  3093.7   205.9  3443.7     206  3863.7     209
  4093.7     207  4123.7   207.9  4163.7   207.6  4223.7   206.1  4253.7     206
  4273.7     207  4374.9   205.9  4654.9   206.3  4784.9   207.4 4995.94  205.19
  4998.7  203.99  4999.9   202.5  5001.3  203.97  5007.7  205.88  5099.8   205.5
  5189.8   206.6  5402.8  210.74  5549.8   211.9  5609.8   211.2  5752.2  212.03
  5979.8   212.5  6139.8   213.9  6238.3  213.51  6449.8   212.7  6492.6   213.5
#Mann= 7 ,-1 , 0
  2713.7     .06       0  2880.3     .05       0 4995.94    .045       0
  5007.7     .05       0  5402.8    .075       0  5752.2     .06       0
  6238.3    .075       0
#XS Ineff= 3 ,-1
  2713.7    3850   209.1    3850    4989   205.2    5011  6492.6   205.2
Permanent Ineff=
       F       F       F
Bank Sta=4995.94,5007.7
XS Rating Curve= 0
Exp/Cntr=.5,.3

Type RM Length L Ch R = 1 ,10234   ,255.3,256.3,257.5
BEGIN DESCRIPTION:
Cross Section XS12.5
END DESCRIPTION:
XS GIS Cut Line= 5
      2999274.94     13945919.46      2997952.85     13944925.08
      2997306.21     13944896.51      2997251.02     13944894.39
      2995882.15     13944805.53
#Sta/Elev= 30
  2686.7   209.1  2704.9  208.98  2936.7     207  3196.7     206  3486.7   206.1
  3726.7   207.7  3796.7     209  3976.7   207.9  4016.7   206.5  4076.7     206
    4341   206.8    4661   206.1    4781   206.9 4995.23  204.79  4998.7  203.28
  4999.9  202.15  5001.3  203.26 5003.71  204.12  5008.3   204.1  5383.5   209.1
  5405.4  210.05  5423.5   210.5  5473.5   210.2  5573.5   211.5  5743.5   211.2
  5753.5   210.5  5923.5   211.5  5953.5   212.2  6230.2  213.57  6415.3   213.3
#Mann= 7 ,-1 , 0
  2686.7     .06       0  2704.9     .05       0 4995.23    .045       0
  5008.3     .05       0  5405.4    .075       0  5743.5     .06       0
  6230.2    .075       0
#XS Ineff= 2 , 0
       0    3800   209.1               0
Permanent Ineff=
       F       F
Bank Sta=4995.23,5003.71
XS Rating Curve= 0
Exp/Cntr=.3,.1

Type RM Length L Ch R = 1 ,9977.7  ,346.78,363.6,355.01
BEGIN DESCRIPTION:
Cross Section XS12
END DESCRIPTION:
XS GIS Cut Line= 3
    2999460.6664   13945666.0999    2997978.9066   13944686.3572
    2996005.0407   13944551.7565
#Sta/Elev= 30
  2540.4   210.5  2800.4   209.1  3270.4     205  3460.4   205.3  3480.4   205.8
  3540.4   205.8  3720.4   206.8  3920.4   208.6  4316.8   210.1  4646.8   208.8
  4977.4  204.84  4993.7  203.66  4998.7  201.46  4999.9  201.24  5007.7  203.35
  5037.4  204.74  5246.8   205.3  5366.8     207  5396.9   208.4  5496.8   208.6
  5546.8   209.2  5617.3   209.1  5676.8   207.7  5686.8   208.1  5846.8   208.8
  5996.8   210.6  6166.8   211.5  6195.8  211.28  6266.8   211.9  6295.2   211.7
#Mann= 7 ,-1 , 0
  2540.4     .05       0  4977.4    .045       0  5037.4     .05       0
  5396.9    .075       0  5617.3     .06       0  6195.8    .075       0
  6295.2      .2       0
#XS Ineff= 2 , 0
       0    4300     210               0
Permanent Ineff=
       F       F
Bank Sta=4977.4,5037.4
XS Rating Curve= 0
Exp/Cntr=.3,.1

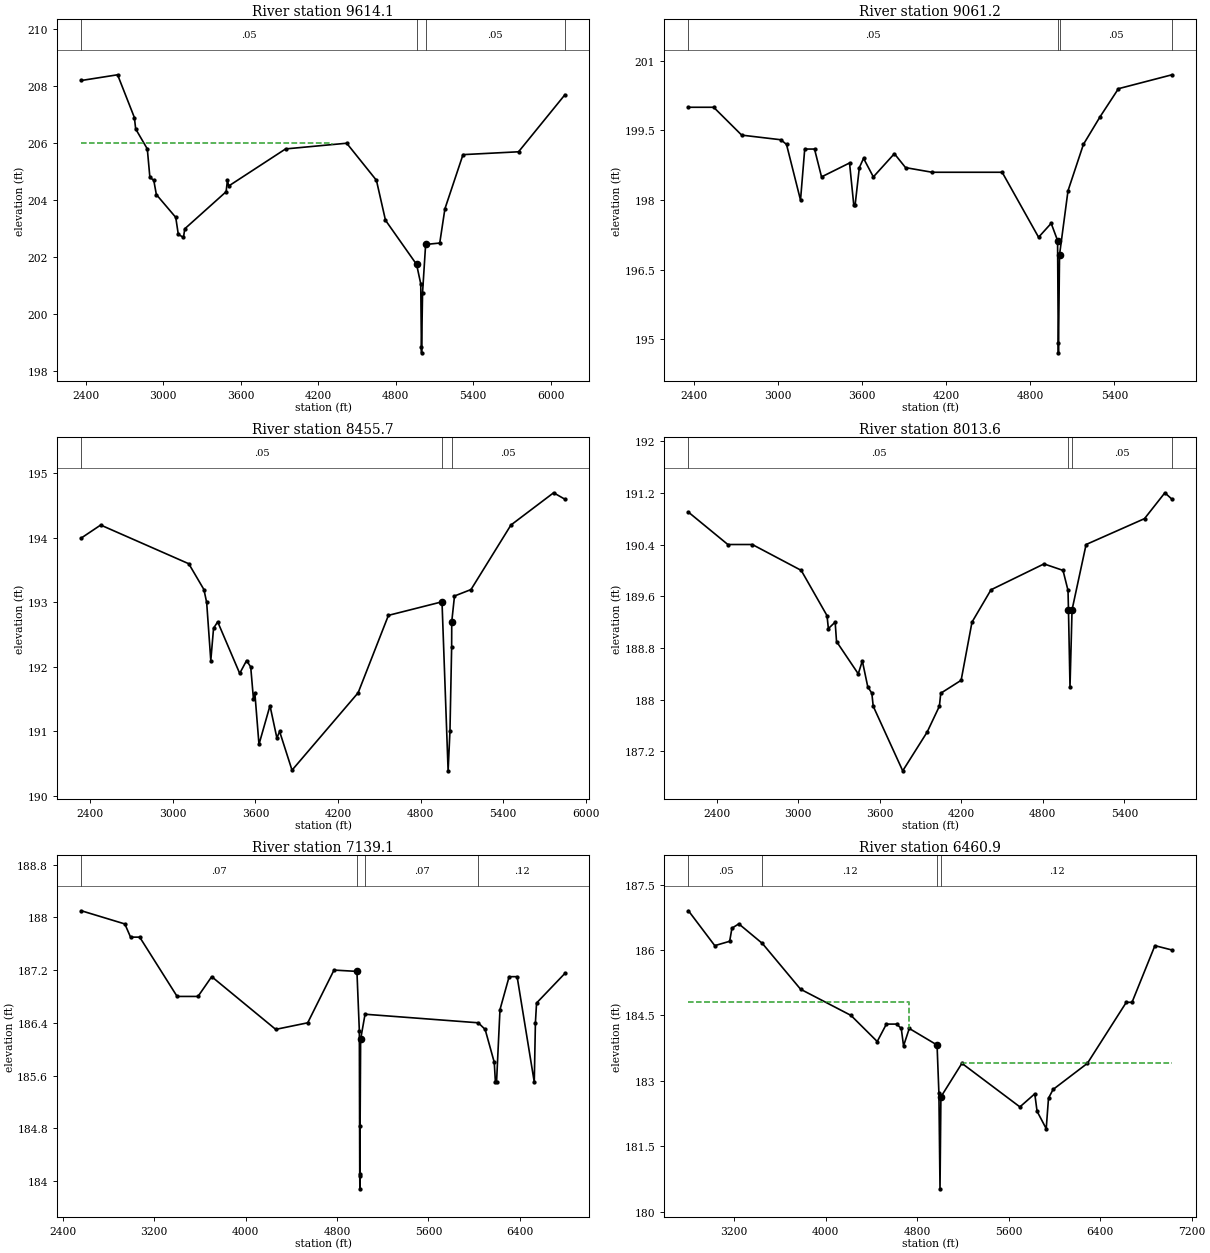
Type RM Length L Ch R = 1 ,9614.1  ,535.08,552.9,555.53
BEGIN DESCRIPTION:
Cross Section XS11.5
END DESCRIPTION:
XS GIS Cut Line= 3
    2999557.8309   13945326.0239    2998067.9742   13944346.2812
    2996114.0142   13944211.2145
#Sta/Elev= 30
  2367.6   208.2  2647.6   208.4  2777.6   206.9  2787.6   206.5  2877.6   205.8
  2897.6   204.8  2927.6   204.7  2947.6   204.2  3097.6   203.4  3117.6   202.8
  3157.6   202.7  3167.6     203  3487.6   204.3  3497.6   204.7  3507.6   204.5
  3947.6   205.8  4420.7     206  4650.7   204.7  4720.7   203.3  4961.5  201.75
  4993.7  201.07  4998.7  198.87  4999.9  198.65  5007.7  200.76  5031.5  202.45
  5140.7   202.5  5180.7   203.7  5320.7   205.6  5750.7   205.7  6109.4   207.7
#Mann= 4 ,-1 , 0
  2367.6     .05       0  4961.5    .045       0  5031.5     .05       0
  6109.4      .2       0
#XS Ineff= 2 , 0
       0    4305     206               0
Permanent Ineff=
       F       F
Bank Sta=4961.5,5031.5
XS Rating Curve= 0
Exp/Cntr=.3,.1

Type RM Length L Ch R = 1 ,9061.2  ,706.19,605.5,595.21
BEGIN DESCRIPTION:
Left ineffective at sta 4470 used to transitions with upstream section
Cross Section XS11
END DESCRIPTION:
XS GIS Cut Line= 3
     2999689.339   13944658.3429    2998131.5542   13943884.1145
    2996440.9345   13943611.8605
#Sta/Elev= 30
  2358.5     200  2538.5     200  2738.5   199.4  3018.5   199.3  3058.5   199.2
  3158.5     198  3188.5   199.1  3258.5   199.1  3308.5   198.5  3508.5   198.8
  3538.5   197.9  3548.5   197.9  3578.5   198.7  3608.5   198.9  3678.5   198.5
  3828.5     199  3908.5   198.7  4098.1   198.6  4598.1   198.6  4858.1   197.2
  4948.1   197.5  4993.7  197.13  4998.7  194.93  4999.9  194.71  5007.7  196.82
  5068.1   198.2  5178.1   199.2  5298.1   199.8  5428.1   200.4  5810.5   200.7
#Mann= 4 ,-1 , 0
  2358.5     .05       0  4993.7    .045       0  5007.7     .05       0
  5810.5      .2       0
#XS Ineff= 2 , 0
       0    4470                       0
Permanent Ineff=
       F       F
Bank Sta=4993.7,5007.7
XS Rating Curve= 0
Exp/Cntr=.3,.1

Type RM Length L Ch R = 1 ,8455.7  ,466.94,442.1,428.05
BEGIN DESCRIPTION:
Left ineffective at sta 4400 used to transitions with upstream section
Cross Section XS10
END DESCRIPTION:
XS GIS Cut Line= 3
     2999904.659   13943775.0038    2998408.0502   13943236.9856
    2996491.9691   13943083.3674
#Sta/Elev= 30
  2335.8     194  2475.8   194.2  3115.8   193.6  3225.8   193.2  3245.8     193
  3275.8   192.1  3295.8   192.6  3325.8   192.7  3485.8   191.9  3535.8   192.1
  3565.8     192  3585.8   191.5  3595.8   191.6  3625.8   190.8  3705.8   191.4
  3755.8   190.9  3775.8     191  3865.8   190.4  4346.2   191.6  4566.2   192.8
  4955.5  193.01  4999.9  190.39  5013.3  191.01  5025.5  192.31  5026.2   192.7
  5046.2   193.1  5166.2   193.2  5456.2   194.2  5766.2   194.7  5848.4   194.6
#Mann= 3 ,-1 , 0
  2335.8     .05       0  4955.5    .045       0  5025.5     .05       0
#XS Ineff= 2 , 0
       0    4400                       0
Permanent Ineff=
       F       F
Bank Sta=4955.5,5026.2
XS Rating Curve= 0
Exp/Cntr=.3,.1

Type RM Length L Ch R = 1 ,8013.6  ,699.4,874.5,978.9
BEGIN DESCRIPTION:
Left ineffective at sta 4100 used to transitions with upstream and dowstream section
Cross Section XS09
END DESCRIPTION:
XS GIS Cut Line= 3
    3000027.4597   13943236.9856    2998529.5059   13942743.0657
    2996547.4821   13942718.5676
#Sta/Elev= 30
  2191.1   190.9  2481.1   190.4  2661.1   190.4  3021.1     190  3211.1   189.3
  3221.1   189.1  3271.1   189.2  3281.1   188.9  3441.1   188.4  3471.1   188.6
  3511.1   188.2  3541.1   188.1  3551.1   187.9  3768.4   186.9  3948.4   187.5
  4038.4   187.9  4048.4   188.1  4198.4   188.3  4278.4   189.2  4418.4   189.7
  4808.4   190.1  4948.4     190  4985.3  189.69 4988.62  189.39  4999.9   188.2
    5015  189.39  5118.4   190.4  5548.4   190.8  5698.4   191.2  5750.6   191.1
#Mann= 4 ,-1 , 0
  2191.1     .05       0 4988.62     .05       0    5015     .05       0
  5750.6      .2       0
#XS Ineff= 2 , 0
       0    4100                       0
Permanent Ineff=
       F       F
Bank Sta=4988.62,5015
XS Rating Curve= 0
Exp/Cntr=.3,.1

Type RM Length L Ch R = 1 ,7139.1  ,819.8,678.2,605.8
BEGIN DESCRIPTION:
Left ineffective at sta 4100 used to transitions with upstream
Cross Section XS08.5
END DESCRIPTION:
XS GIS Cut Line= 6
    2999911.2671   13942673.5237    2997667.8918    13942112.148
    2997613.9423   13942056.0564    2997546.1614   13941995.2873
    2997480.0123       13941933.       2995842.8      13941670.8
#Sta/Elev= 30
  2563.5   188.1  2943.5   187.9  2993.5   187.7  3073.5   187.7 3400.94   186.8
  3583.5   186.8  3703.5   187.1  4263.5   186.3  4543.5   186.4  4773.5   187.2
  4974.1  187.18 4995.17  186.28  4998.7   184.1  4999.9  183.88  5000.5  184.07
 5001.83  184.83  5006.5  186.15 5045.18  186.53  6035.7   186.4  6095.7   186.3
  6175.7   185.8  6185.7   185.5  6195.7   185.5  6225.7   186.6  6305.7   187.1
  6375.7   187.1  6525.7   185.5  6535.7   186.4  6545.7   186.7 6793.84  187.15
#Mann= 4 ,-1 , 0
  2563.5     .07       0  4974.1    .065       0 5045.18     .07       0
  6035.7     .12       0
#XS Ineff= 2 , 0
       0    4100                       0
Permanent Ineff=
       F       F
Bank Sta=4974.1,5006.5
XS Rating Curve= 0
Exp/Cntr=.3,.1

Type RM Length L Ch R = 1 ,6460.9  ,1554.28,1407.9,1330.65
BEGIN DESCRIPTION:
Cross Section XS08
END DESCRIPTION:
XS GIS Cut Line= 3
    3000122.9562   13942018.8341    2997444.9286   13941363.5097
      2996021.27     13941000.62
#Sta/Elev= 30
  2801.2   186.9  3031.2   186.1  3161.2   186.2  3181.2   186.5  3241.2   186.6
  3447.5  186.15  3781.2   185.1  4221.2   184.5  4451.2   183.9  4531.2   184.3
  4621.2   184.3  4661.2   184.2  4681.2   183.8  4731.2   184.2  4974.1  183.82
  4990.3  182.71  4999.9  180.52  5007.7  182.63  5191.2   183.4  5698.2   182.4
  5828.2   182.7  5848.2   182.3  5928.2   181.9  5948.2   182.6  5988.2   182.8
  6288.2   183.4  6628.2   184.8  6678.2   184.8  6878.2   186.1  7027.4     186
#Mann= 4 ,-1 , 0
  2801.2     .05       0  3447.5     .12       0  4974.1    .075       0
  5007.7     .12       0
#XS Ineff= 2 , 0
       0    4732   184.8    5190       0   183.4
Permanent Ineff=
       F       F
#Block Obstruct= 2 , 0
       0                    5190       0   183.4
Bank Sta=4974.1,5007.7
XS Rating Curve= 0
Exp/Cntr=.3,.1

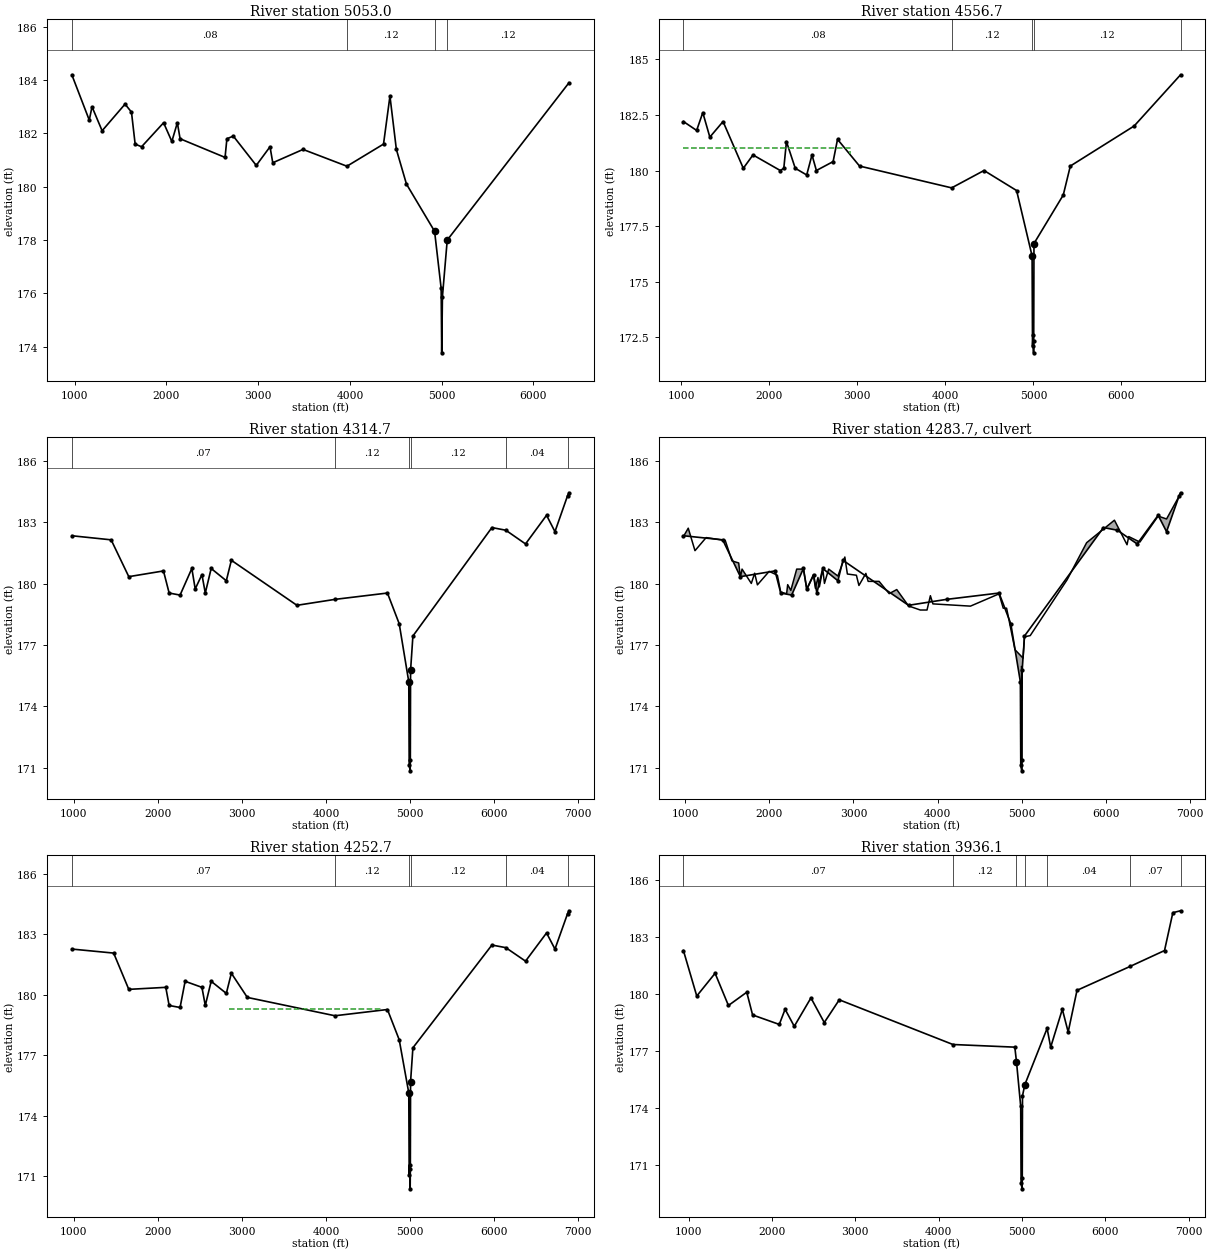
Type RM Length L Ch R = 1 ,5053.0  ,431.6,496.3,469.9
BEGIN DESCRIPTION:
Cross Section XS07
END DESCRIPTION:
XS GIS Cut Line= 3
      3002440.13     13941091.92      2999718.92     13940289.43
      2997140.12     13940178.06
#Sta/Elev= 30
   968.5   184.2  1158.5   182.5  1188.5     183  1298.5   182.1  1548.5   183.1
  1618.5   182.8  1658.5   181.6  1728.5   181.5  1968.5   182.4  2058.5   181.7
  2118.5   182.4  2148.5   181.8  2638.5   181.1  2658.5   181.8  2728.5   181.9
  2978.5   180.8  3128.5   181.5  3158.5   180.9  3488.5   181.4  3966.8  180.77
  4365.6   181.6  4435.6   183.4  4505.6   181.4  4615.6   180.1  4922.1  178.33
  4993.7  176.19  4999.9  173.77  5007.7  175.88    5060     178  6386.8   183.9
#Mann= 4 ,-1 , 0
   968.5     .08       0  3966.8     .12       0  4922.1    .075       0
    5060     .12       0
#XS Ineff= 2 , 0
       0    4425   181.9               0
Permanent Ineff=
       F       F
Bank Sta=4922.1,5060
XS Rating Curve= 0
Exp/Cntr=.3,.1

Type RM Length L Ch R = 1 ,4556.7  ,182.6,242,215.3
BEGIN DESCRIPTION:
Cross Section XS06
END DESCRIPTION:
XS GIS Cut Line= 4
      3002446.45     13940820.04    2999772.5618    13939851.354
    2997748.0542   13939804.8816      2996978.71     13939912.92
#Sta/Elev= 30
  1025.4   182.2  1175.4   181.8  1245.4   182.6  1325.4   181.5  1475.4   182.2
  1705.4   180.1  1815.4   180.7  2125.4     180  2165.4   180.1  2195.4   181.3
  2295.4   180.1  2425.4   179.8  2485.4   180.7  2535.4     180  2725.4   180.4
  2775.4   181.4  3025.4   180.2  4071.6  179.22  4439.3     180  4809.3   179.1
  4985.2  176.16    4990   172.1  4996.4  172.59  5001.8  171.81  5003.6  172.36
  5006.5  176.72  5339.3   178.9  5419.3   180.2  6144.4     182  6671.3   184.3
#Mann= 5 ,-1 , 0
  1025.4     .08       0  4071.6     .12       0  4985.2    .065       0
  5006.5     .12       0  6671.3      .2       0
#XS Ineff= 2 ,-1
    1000    2915     181    2915    4432   179.9
Permanent Ineff=
       F       F
Bank Sta=4985.2,5006.5
XS Rating Curve= 0
Exp/Cntr=.5,.3

Type RM Length L Ch R = 1 ,4314.7  ,62,62,62
BEGIN DESCRIPTION:
Upstream Section of Bridge/Culvert/Weir
END DESCRIPTION:
XS GIS Cut Line= 6
    3002497.0333   13940737.8431    2999736.8375   13939706.1068
    2998896.0521   13939724.5091    2998506.3013   13939637.2515
    2997754.5072   13939671.3228    2996856.2219   13939822.9446
#Sta/Elev= 30
   977.4  182.34  1444.8  182.14  1654.8  180.34  2067.4  180.62  2134.8  179.54
  2264.8  179.44  2404.8  180.74  2444.8  179.74  2524.8  180.44  2564.8  179.54
  2634.8  180.74  2814.8  180.14  2874.8  181.14  3654.8  178.94  4106.9  179.23
  4731.3  179.54  4871.3  178.04  4985.2   175.2    4990  171.14  5001.8  170.85
  5003.6   171.4  5006.5  175.76  5034.2  177.44  5973.9  182.74  6139.2  182.61
  6373.9  181.94  6623.9  183.34  6723.9  182.54  6874.1   184.3  6890.5  184.44
#Mann= 6 ,-1 , 0
   977.4     .07       0  4106.9     .12       0  4985.2    .065       0
  5006.5     .12       0  6139.2     .04       0  6874.1      .2       0
#XS Ineff= 4 ,-1
   977.4    2850   180.5    2850    4670   179.5    4670    4870   176.4
    5050  6890.5   176.4
Permanent Ineff=
       F       F       F       F
Bank Sta=4985.2,5006.5
XS Rating Curve= 0
Exp/Cntr=.5,.3

Type RM Length L Ch R = 2 ,4283.7  ,,,
BEGIN DESCRIPTION:
CULVERT 750' U/S BAUER HOCKLEY "60P CMP ST"
Structure ID: L112-00-00-S2
END DESCRIPTION:
Bridge Culvert--1,0,-1,-1, 0
Deck Dist Width WeirC Skew NumUp NumDn MinLoCord MaxHiCord MaxSubmerge Is_Ogee
10,42,2.6,0, 60, 60, , , .95, 0, 1,1,,
   977.4  1034.8  1114.8  1247.4  1474.8  1554.8  1634.8  1654.8  1674.8  1784.8
  1824.8  1857.4  1997.4  2094.8  2134.8  2204.8  2217.4  2254.8  2324.8  2404.8
  2444.8  2524.8  2547.4  2577.4  2594.8  2634.8  2654.8  2704.8  2814.8  2897.4
  2927.4  3034.8  3064.8  3147.4  3174.8  3304.8  3424.8  3514.8  3654.8  3794.8
  3874.8  3914.8  3944.8  4391.3  4731.3  4781.3  4821.3  4921.2    5017  5034.2
  5102.3  5541.3  5773.2  6103.9  6253.9  6273.9  6406.5  6623.9  6723.9  6890.5
   182.3  182.71  181.61  182.25  182.11  181.11  181.01  180.31  180.71  180.01
  180.51  179.94   180.6  180.41  179.58  179.51  179.95  179.67  180.71  180.71
  179.71  180.41  179.77   180.3  179.84  180.71  180.01  180.71  180.37   181.3
  180.47  180.41  179.91   180.5  180.11  180.11  179.51  179.71  178.91  178.71
  178.71  179.41  179.01   178.9   179.5   178.8   178.8  176.77  176.36   177.4
  177.46  180.19     182   183.1   181.9   182.3  182.03   183.3  183.16   184.4
                                                                                
                                                                                
                                                                                
                                                                                
                                                                                
                                                                                
   977.4  1034.8  1114.8  1247.4  1474.8  1554.8  1634.8  1654.8  1674.8  1784.8
  1824.8  1857.4  1997.4  2094.8  2134.8  2204.8  2217.4  2254.8  2324.8  2404.8
  2444.8  2524.8  2547.4  2577.4  2594.8  2634.8  2654.8  2704.8  2814.8  2854.8
  2897.4  2927.4  3034.8  3064.8  3147.4  3174.8  3304.8  3424.8  3514.8  3644.8
  3654.8  3794.8  3834.8  3874.8  3914.8  3944.8  4391.3  4731.3  4781.3  4821.3
  4921.2    5017  5034.2  5301.3  5773.2  6103.9  6253.9  6273.9  6423.9  6890.5
   182.3  182.71  181.61  182.25  182.11  181.11  181.01  180.31  180.71  180.01
  180.51  179.94   180.6  180.41  179.58  179.51  179.95  179.67  180.71  180.71
  179.71  180.41  179.77   180.3  179.84  180.71  180.01  180.71  180.37  181.11
   181.3  180.47  180.41  179.91   180.5  180.11  180.11  179.51  179.71  179.31
  178.91  178.71  179.01  178.71  179.41  179.01  178.71  179.31  178.61  178.61
  176.77  176.36  177.21  178.51     182  182.91  181.71  182.11  181.93   184.2
                                                                                
                                                                                
                                                                                
                                                                                
                                                                                
                                                                                
BR Coef= 1 , 0 , 0 ,1.25, 0 ,,,.8,-1,2,0,
WSPro=,,,, 1 ,,,, 0 ,,,, 0 ,,,,-1 ,-1 ,-1 , 0 , 0 , 0 , 0 , 0
Culvert=1,5,,42,.015,.5,1,1,3,170.98,4999.2,170.81,4999.2,Culvert #1  , 0 ,10
Culvert Bottom n=.015
BC Design=,, 0 ,, 0 ,,,,,,
BC HTab HWMax=184.44

Type RM Length L Ch R = 1 ,4252.7  ,316.6,316.6,316.6
BEGIN DESCRIPTION:
Downstream Section of Bridge/Culvert/Weir
END DESCRIPTION:
XS GIS Cut Line= 6
     3002503.356   13940643.0016    2999718.9175   13939577.3064
    2998920.6898   13939646.8793    2998521.1491   13939540.7513
    2997735.6416   13939581.0936    2996802.3797    13939665.252
#Sta/Elev= 30
   977.4  182.27  1474.8  182.07  1654.8  180.27  2094.8  180.37  2134.8  179.47
  2264.8  179.37  2324.8  180.67  2524.8  180.37  2564.8  179.47  2634.8  180.67
  2814.8  180.07  2874.8  181.07  3064.8  179.87  4106.9  178.96  4731.3  179.27
  4871.3  177.77  4985.2  175.13    4990  171.07  4996.4  171.56  5001.8  170.37
  5003.6  171.33  5006.5  175.69  5034.2  177.37  5973.9  182.47  6139.2  182.34
  6373.9  181.67  6623.9  183.07  6723.9  182.27  6874.1  184.03  6890.5  184.17
#Mann= 6 ,-1 , 0
   977.4     .07       0  4106.9     .12       0  4985.2    .065       0
  5006.5     .12       0  6139.2     .04       0  6874.1      .2       0
#XS Ineff= 4 ,-1
   977.4    2850   180.5    2850    4670   179.3    4670    4870   176.4
    5050  6890.5   176.4
Permanent Ineff=
       F       F       F       F
Bank Sta=4985.2,5006.5
XS Rating Curve= 0
Exp/Cntr=.5,.3

Type RM Length L Ch R = 1 ,3936.1  ,234.49,232.1,181.74
BEGIN DESCRIPTION:
Cross Section XS05
END DESCRIPTION:
XS GIS Cut Line= 4
      3002572.91     13940560.81    2999772.5618   13939386.4364
    2998094.0883   13939226.0943     2996856.337   13939334.0045
#Sta/Elev= 30
     938   182.3    1098   179.9    1318   181.1    1478   179.4    1698   180.1
    1768   178.9    2088   178.4    2158   179.2    2268   178.3    2468   179.8
    2628   178.5    2808   179.7  4171.9  177.34  4914.6   177.2  4934.6  176.42
  4985.2  174.07    4990  170.01  5001.8  169.72  5003.6  170.27  5006.5  174.63
  5034.5  175.22  5301.9  178.19  5344.6   177.2  5484.6   179.2  5554.6     178
  5660.7   180.2  6296.8  181.46  6710.7   182.3  6810.7   184.3  6903.2   184.4
#Mann= 7 ,-1 , 0
     938     .07       0  4171.9     .12       0  4934.6    .065       0
  5034.5     .12       0  5301.9     .04       0  6296.8     .07       0
  6903.2      .2       0
#XS Ineff= 2 , 0
       0    2800   179.3               0
Permanent Ineff=
       F       F
Bank Sta=4934.6,5034.5
XS Rating Curve= 0
Exp/Cntr=.3,.1