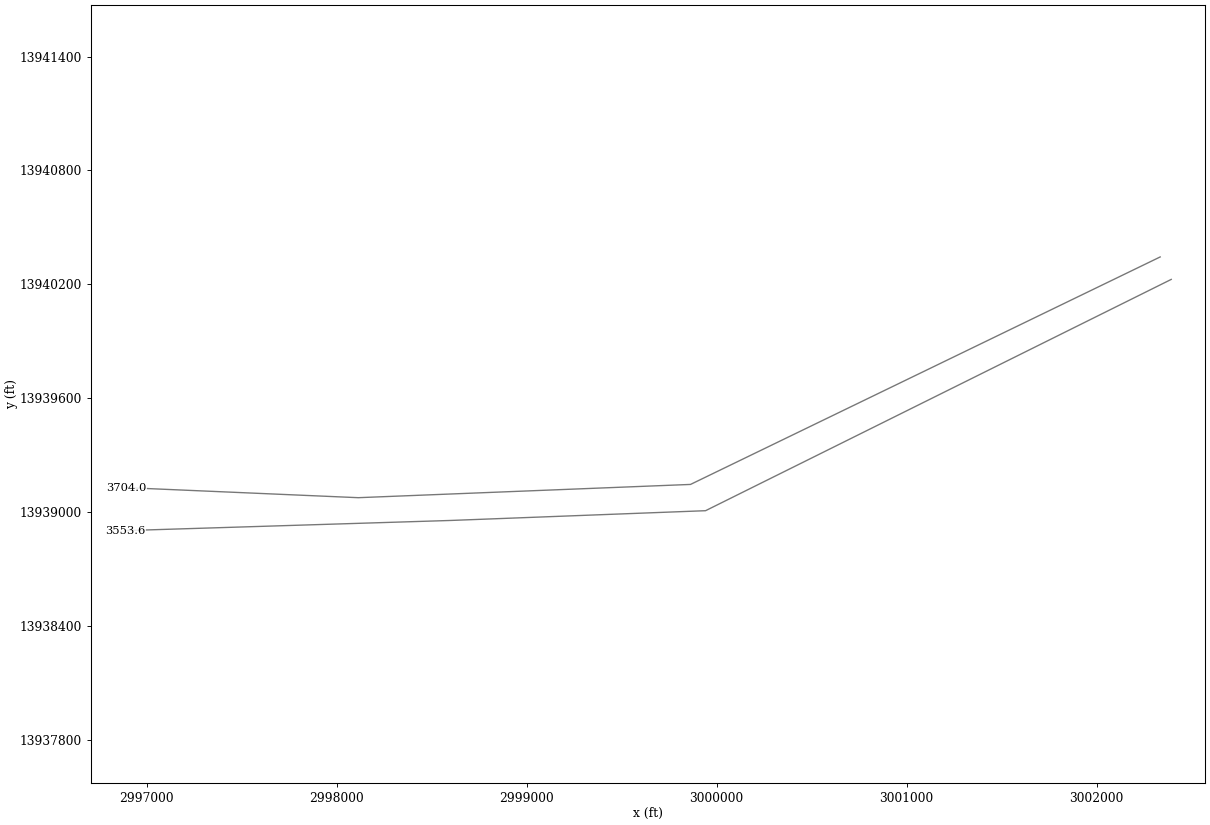
HEC-RAS study L112-00-00.PRJ: L112-00-00

--- L112-00-00.g01 (geometry) --- (continued)

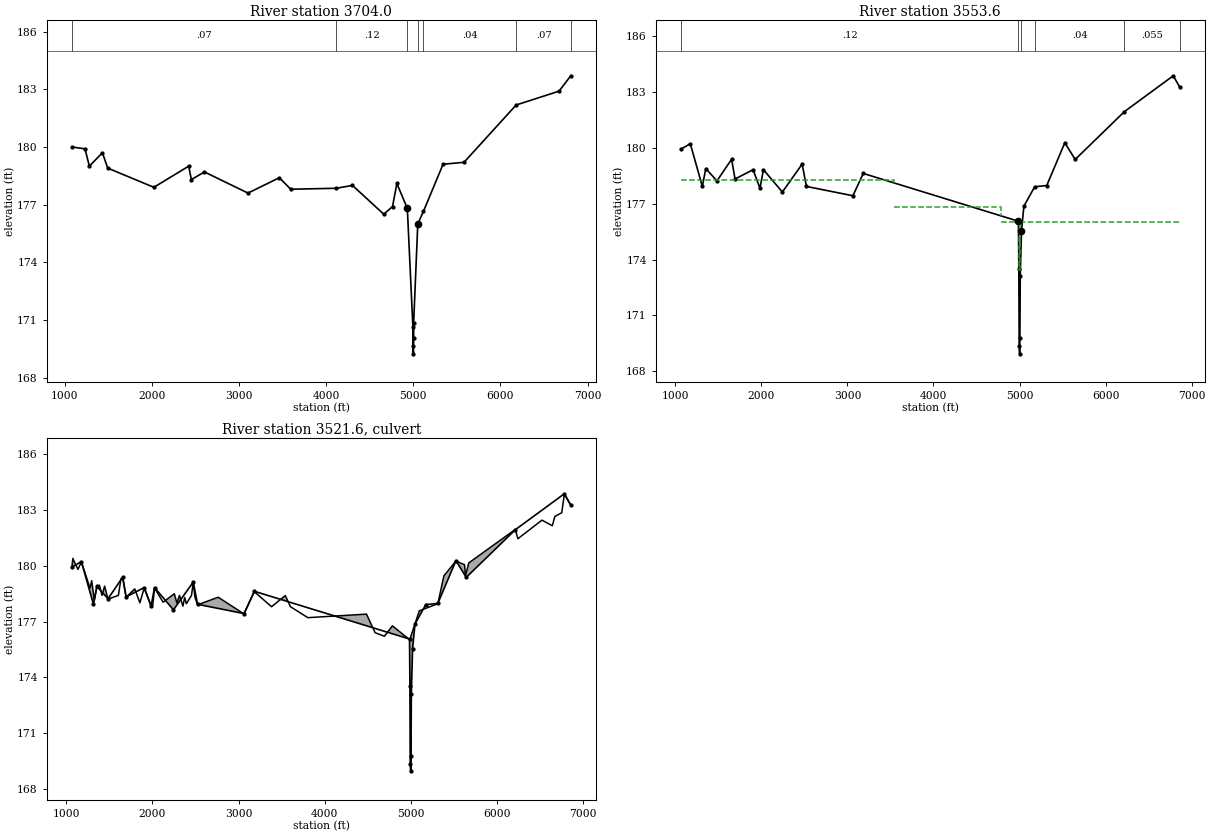
Type RM Length L Ch R = 1 ,3704.0  ,149.33,150.4,140.9
BEGIN DESCRIPTION:
Cross Section XS04
END DESCRIPTION:
XS GIS Cut Line= 4
      3002334.76     13940343.98    2999861.9691   13939145.0368
    2998112.9539   13939075.1693    2996889.6582   13939128.1933
#Sta/Elev= 30
  1083.8     180  1233.8   179.9  1283.8     179  1433.8   179.7  1493.8   178.9
  2023.8   177.9  2423.8     179  2453.8   178.3  2603.8   178.7  3103.8   177.6
  3463.8   178.4  3593.8   177.8    4117  177.85  4301.9     178  4661.9   176.5
  4761.9   176.9  4811.9   178.1  4931.8   176.8  4995.5  170.66    4996  169.66
  5001.5  169.24  5004.3  170.08  5004.6  170.86  5051.8     176  5116.7  176.65
  5341.9   179.1  5582.3   179.2  6180.1  182.18  6672.3   182.9  6806.8   183.7
#Mann= 7 ,-1 , 0
  1083.8     .07       0    4117     .12       0  4931.8    .065       0
  5051.8     .12       0  5116.7     .04       0  6180.1     .07       0
  6806.8      .2       0
#XS Ineff= 2 ,-1
    1000    2425   178.8    2425    4820   177.9
Permanent Ineff=
       F       F
Bank Sta=4931.8,5051.8
XS Rating Curve= 0
Exp/Cntr=.5,.3

Type RM Length L Ch R = 1 ,3553.6  ,64,64,64
BEGIN DESCRIPTION:
Upstream Section of Bridge/Culvert/Weir
END DESCRIPTION:
XS GIS Cut Line= 4
    3002392.9627   13940225.5718    2999941.2323   13939006.5899
    2998601.4019   13938955.2375    2996887.7695   13938901.6865
#Sta/Elev= 30
  1063.6  179.93  1173.6  180.23  1313.6  177.93  1353.7  178.89  1483.6  178.23
  1653.7  179.39  1693.6  178.33  1903.6  178.83  1983.6  177.83  2023.7  178.83
  2243.6  177.63  2473.6  179.13  2523.6  177.93  3063.7  177.43  3183.6  178.63
  4987.2  176.06  4991.9  173.51    4996  169.35  5001.5  168.93  5004.3  169.77
  5008.4  173.12  5022.7  175.55    5051  176.87  5175.7  177.91  5316.5  177.98
  5526.5  180.28  5646.5  179.38  6218.2  181.95  6786.5  183.88  6861.1  183.28
#Mann= 6 ,-1 , 0
  1063.6     .12       0  4987.2    .065       0  5022.7    .065       0
  5175.7     .04       0  6218.2    .055       0  6861.1      .2       0
#XS Ineff= 4 ,-1
  1063.6    3540   178.3    3540    4786   176.8    4786    4992     176
    5010  6861.1     176
Permanent Ineff=
       F       F       F       F
Bank Sta=4987.2,5022.7
XS Rating Curve= 0
Exp/Cntr=.5,.3

Type RM Length L Ch R = 2 ,3521.6  ,,,
BEGIN DESCRIPTION:
BAUER-HOCKLEY RD
Structure ID: L112-00-00-S01
END DESCRIPTION:
Bridge Culvert--1,0,-1,-1, 0
Deck Dist Width WeirC Skew NumUp NumDn MinLoCord MaxHiCord MaxSubmerge Is_Ogee
10,44,2.6,0, 60, 60, , , .95, 0, 1,1,,
  1063.6  1073.7  1133.6  1173.6  1273.7  1293.7  1323.7  1353.7  1383.7  1413.6
  1443.6  1483.6  1603.6  1633.7  1653.7  1693.6  1793.7  1853.7  1903.6  1983.6
  2003.7  2023.7  2123.7  2253.7  2283.7  2313.7  2353.6  2373.7  2393.7  2453.6
  2473.6  2493.6  2523.6  2763.6  3063.7  3183.6  3383.6  3543.7  3603.6  3805.7
  4487.4  4587.4  4695.7  4788.2  4989.5  5101.1  5316.5  5386.5  5526.5  5626.5
  5636.5  5676.5  6216.5  6246.5  6526.5  6646.5  6676.5  6756.5  6786.5  6861.1
   179.9   180.4  179.81  180.21   178.8   179.2  178.15  178.87  178.96  178.41
  178.91  178.21  178.41  179.31  179.37  178.31  178.76  178.01  178.81  177.85
  177.91  178.81  178.04   178.5     178  178.41  177.83   178.3  177.96  178.41
  179.11  178.31   177.9  178.31  177.41  178.61   177.8   178.4   177.8  177.21
   177.4   176.4  176.21  176.77  176.02  177.58  177.96  179.46  180.26  180.06
  179.46  180.16  181.96  181.46  182.46  182.16  182.66  182.86  183.86  183.26
                                                                                
                                                                                
                                                                                
                                                                                
                                                                                
                                                                                
  1063.6  1073.7  1133.6  1173.6  1273.7  1293.7  1323.7  1353.7  1383.7  1413.6
  1443.6  1483.6  1603.6  1633.7  1653.7  1693.6  1793.7  1853.7  1903.6  1983.6
  2003.7  2023.7  2123.7  2253.7  2313.7  2353.6  2373.7  2393.7  2453.6  2473.6
  2493.6  2523.6  2763.6  3063.7  3183.6  3383.6  3543.7  3603.6  3805.7  4487.4
  4587.4  4695.7  4788.2  4987.2  5101.1  5314.5  5386.5  5526.5  5626.5  5636.5
  5664.5  6006.5  6216.5  6246.5  6526.5    6642    6692  6756.5  6786.5  6861.1
   179.9   180.4  179.81  180.21   178.8   179.2  178.15  178.87  178.96  178.41
  178.91  178.21  178.41  179.31  179.37  178.31  178.76  178.01  178.81  177.85
  177.91  178.81  178.04   178.5  178.41  177.83   178.3  177.96  178.41  179.11
  178.31   177.9  178.31  177.41  178.61   177.8   178.4   177.8  177.21   177.4
   176.4  176.21  176.77  176.02  177.33   177.9  179.21  180.01  179.81  179.39
   180.1  180.71  181.71  181.21  182.21     182   182.7  182.61  183.61     183
                                                                                
                                                                                
                                                                                
                                                                                
                                                                                
                                                                                
BR Coef= 1 , 0 , 0 ,1.25, 0 ,,,.8,-1,2,0,
WSPro=,,,, 1 ,,,, 0 ,,,, 0 ,,,,-1 ,-1 ,-1 , 0 , 0 , 0 , 0 , 0
Culvert=1,5,,44,.015,.5,1,1,3,168.91,5001.1,168.38,5001.1,Culvert #1  , 0 ,10
Culvert Bottom n=.015
BC Design=,, 0 ,, 0 ,,,,,,
BC HTab HWMax=183.88