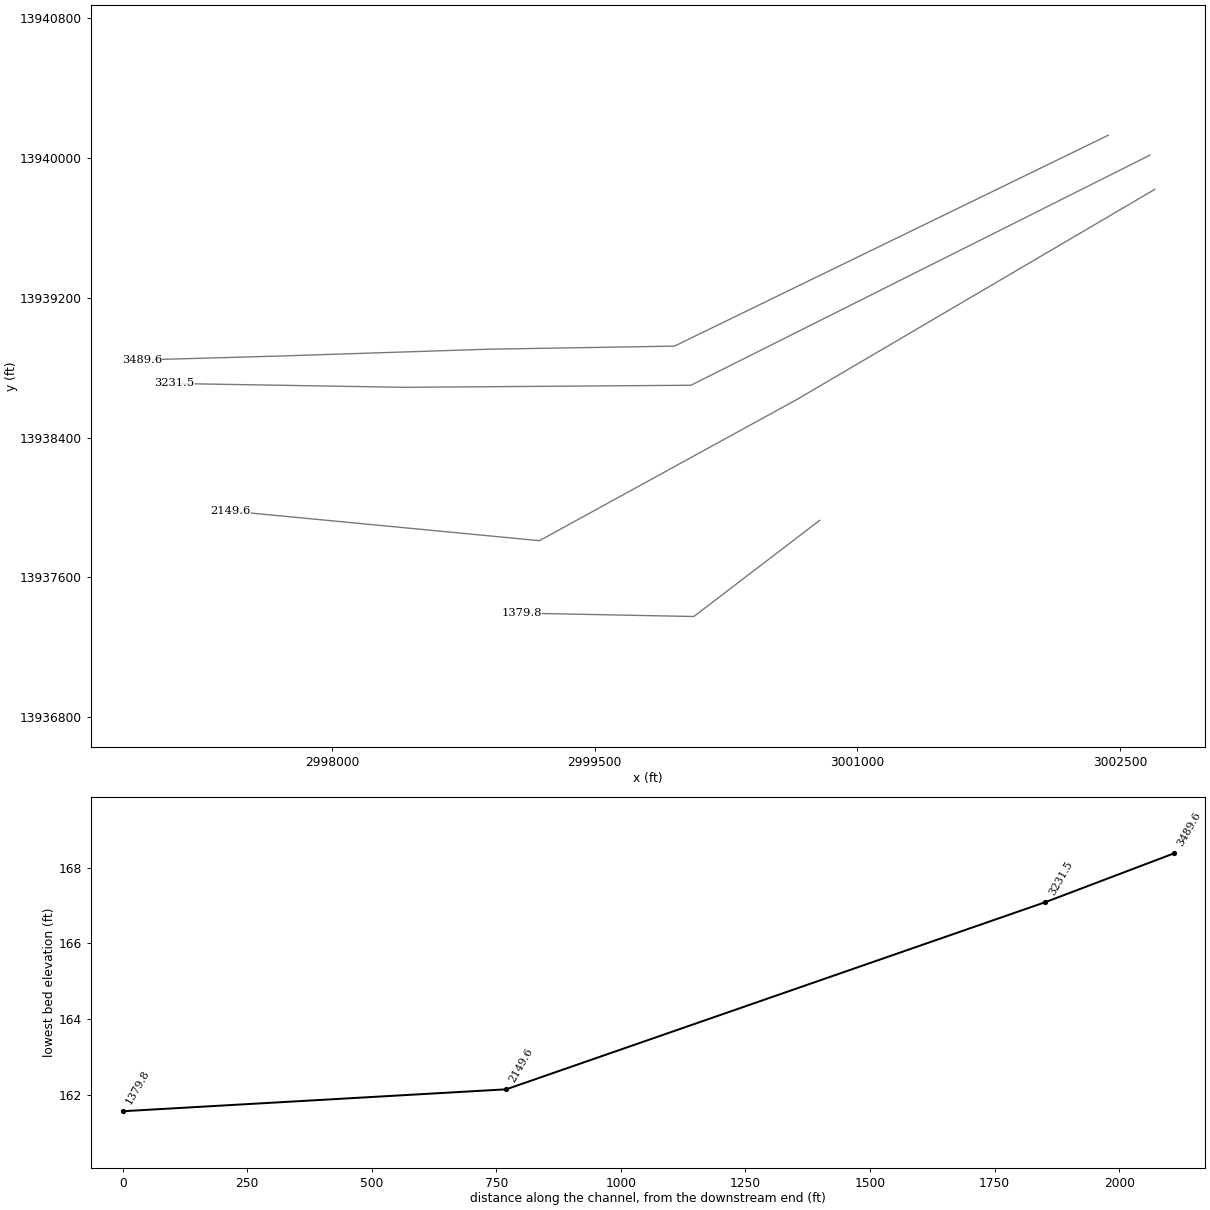
HEC-RAS study L112-00-00.PRJ: L112-00-00

--- L112-00-00.g01 (geometry) --- (continued)

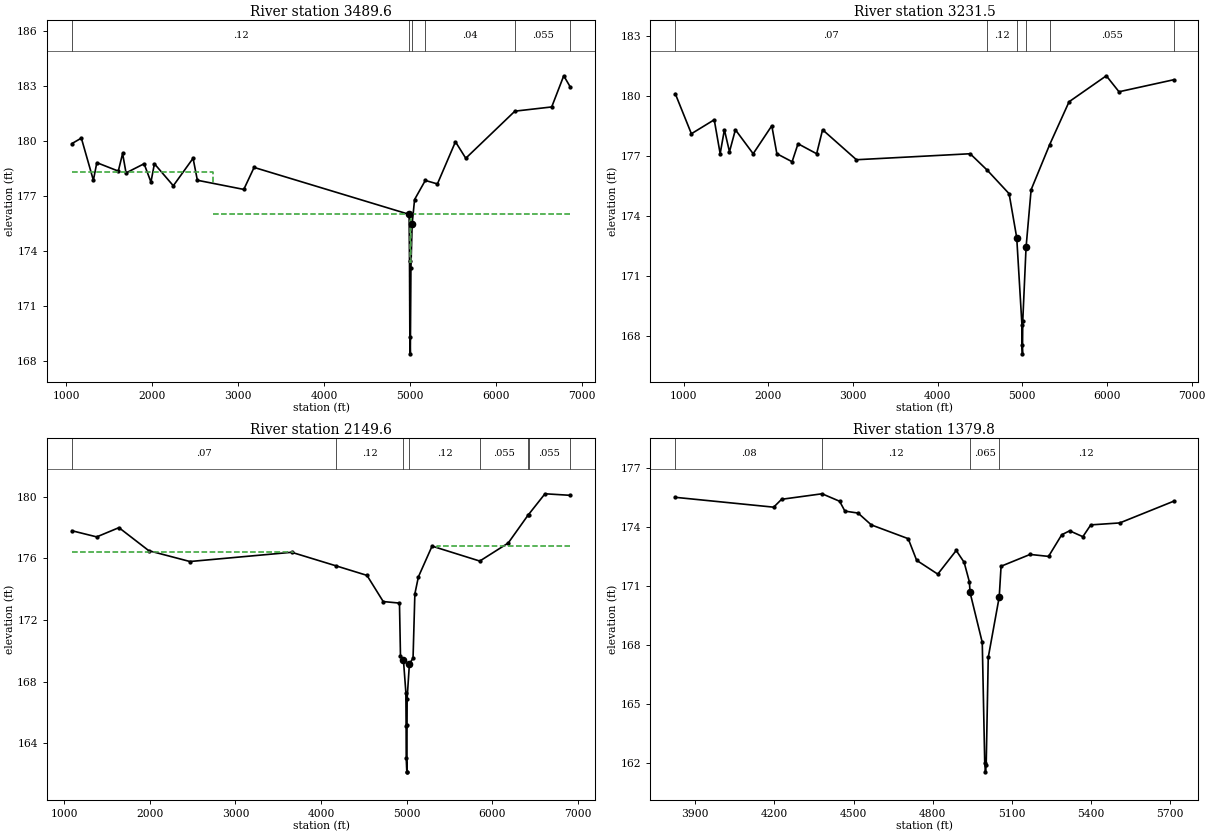
Type RM Length L Ch R = 1 ,3489.6  ,245.1,258.1,223.1
BEGIN DESCRIPTION:
Downstream Section of Bridge/Culvert/Weir
END DESCRIPTION:
XS GIS Cut Line= 5
    3002434.2418   13940131.2195    2999955.3653   13938923.6362
    2998888.5048   13938905.8867    2997691.5907   13938866.6163
    2996912.4364    13938844.731
#Sta/Elev= 30
  1063.6  179.85  1173.6  180.15  1313.6  177.85  1353.7  178.81  1603.6  178.35
  1653.7  179.31  1693.6  178.25  1903.6  178.75  1983.6  177.75  2023.7  178.75
  2243.6  177.55  2473.6  179.05  2523.6  177.85  3063.7  177.35  3183.6  178.55
  4987.2  175.99  4991.9  173.44    4996  169.28  5001.5  168.38  5008.4  173.05
  5022.7  175.48    5051   176.8  5175.7  177.84  5316.5  177.65  5526.5  179.95
  5646.5  179.05  6218.2  181.62  6646.5  181.85  6786.5  183.55  6861.1  182.95
#Mann= 6 ,-1 , 0
  1063.6     .12       0  4987.2    .065       0  5022.7    .065       0
  5175.7     .04       0  6218.2    .055       0  6861.1      .2       0
#XS Ineff= 3 ,-1
  1063.6    2700   178.3    2700    4992     176    5010  6861.1     176
Permanent Ineff=
       F       F       F
Bank Sta=4987.2,5022.7
XS Rating Curve= 0
Exp/Cntr=.5,.3

Type RM Length L Ch R = 1 ,3231.5  ,800.98,1081.9,1004.69
BEGIN DESCRIPTION:
Cross Section XS03
END DESCRIPTION:
XS GIS Cut Line= 4
    3002671.2592   13940016.7238    3000049.5837   13938699.6108
    2998411.3259   13938687.7965      2997096.82      13938709.7
#Sta/Elev= 30
   899.7   180.1  1089.7   178.1  1359.7   178.8  1429.7   177.1  1479.7   178.3
  1539.7   177.2  1609.7   178.3  1819.7   177.1  2039.7   178.5  2099.7   177.1
  2279.7   176.7  2349.7   177.6  2569.7   177.1  2639.7   178.3  3039.7   176.8
  4383.5   177.1  4586.8  176.27  4843.5   175.1  4933.5   172.9  4995.5  168.51
    4996  167.51  5001.5  167.09  5004.6  168.71  5043.6  172.41  5103.5   175.3
  5323.2  177.56  5551.8   179.7  5991.8     181  6141.8   180.2  6786.5   180.8
#Mann= 6 ,-1 , 0
   899.7     .07       0  4586.8     .12       0  4933.5    .065       0
  5043.6     .12       0  5323.2    .055       0  6786.5      .2       0
#XS Ineff= 2 , 0
       0    2630   177.5               0
Permanent Ineff=
       F       F
Bank Sta=4933.5,5043.6
XS Rating Curve= 0
Exp/Cntr=.3,.1

Type RM Length L Ch R = 1 ,2149.6  ,762.81,769.8,586.71
BEGIN DESCRIPTION:
Cross Section XS02
END DESCRIPTION:
XS GIS Cut Line= 4
      3002699.36     13939821.04       3000657.2     13938619.55
    2999184.1025   13937809.7964    2997417.9447   13937979.3286
#Sta/Elev= 30
  1087.5   177.8  1377.5   177.4  1637.5     178  1987.5   176.5  2467.5   175.8
  3656.9   176.4  4174.9  175.52  4536.9   174.9  4726.9   173.2  4916.9   173.1
  4928.7  169.67  4962.9  169.43  4991.7  167.29  4994.6   165.1  4995.8  163.02
  5002.7  162.14  5003.6  162.14  5005.1  165.17  5006.6   166.9    5033  169.16
  5075.6  169.52  5096.9   173.7  5137.9   174.8  5297.9   176.8  5855.6  175.83
  6187.9     177  6423.6  178.84  6425.7  178.85  6617.9   180.2  6912.2   180.1
#Mann= 8 ,-1 , 0
  1087.5     .07       0  4174.9     .12       0  4962.9    .065       0
    5033     .12       0  5855.6    .055       0  6423.6      .1       0
  6425.7    .055       0  6912.2      .2       0
#XS Ineff= 2 , 0
       0    3675   176.4    5360       0   176.8
Permanent Ineff=
       F       F
Bank Sta=4962.9,5033
XS Rating Curve= 0
Exp/Cntr=.3,.1

Type RM Length L Ch R = 1 ,1379.8  ,0,0,0
BEGIN DESCRIPTION:
Cross Section XS01
END DESCRIPTION:
XS GIS Cut Line= 3
      3000784.62      13937925.8    3000066.1739    13937375.629
       2999082.5      13937395.1
#Sta/Elev= 30
  3824.2   175.5  4197.1     175  4227.1   175.4  4380.6  175.68  4447.1   175.3
  4467.1   174.8  4517.1   174.7  4567.1   174.1  4707.1   173.4  4739.1   172.3
  4819.1   171.6  4889.1   172.8  4919.1   172.2  4939.1   171.2  4941.5  170.67
  4987.8  168.13  4997.2  161.99    5000  161.56  5002.7  161.91  5010.5  167.37
  5052.1  170.44  5059.1     172  5169.1   172.6  5239.1   172.5  5289.1   173.6
  5319.1   173.8  5369.1   173.5  5399.1   174.1  5509.1   174.2    5713   175.3
#Mann= 4 ,-1 , 0
  3824.2     .08       0  4380.6     .12       0  4941.5    .065       0
  5052.1     .12       0
Bank Sta=4941.5,5052.1
XS Rating Curve= 0
Exp/Cntr=.3,.1

Chan Stop Cuts=-1